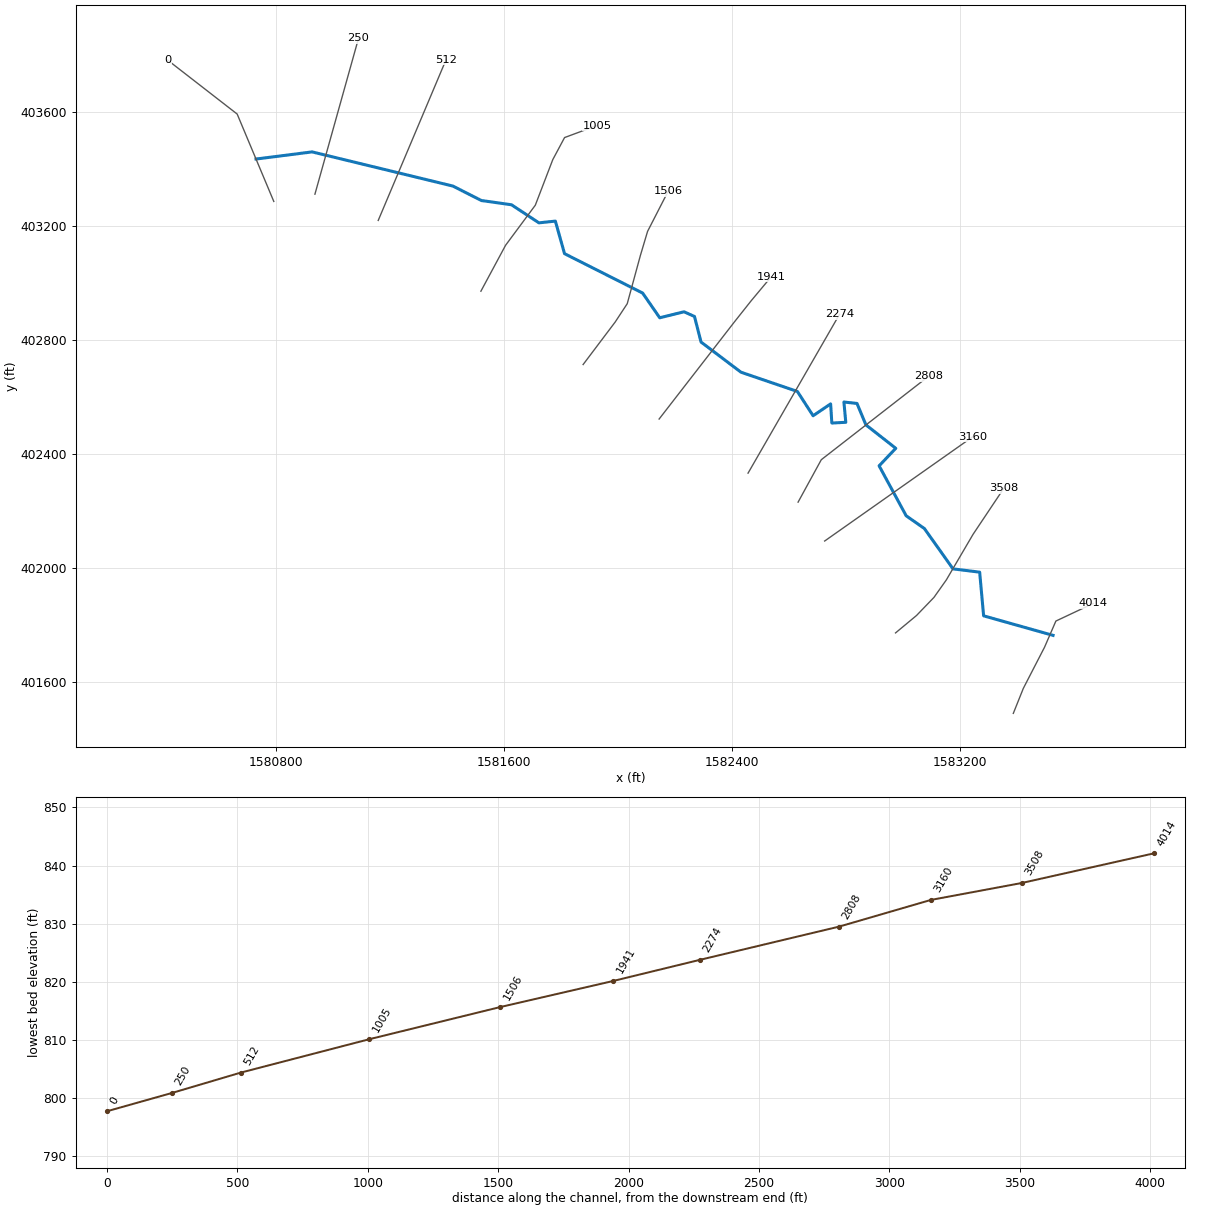
--- PEACHFK.prj (project) ---

Proj Title=PEACHFK
Current Plan=p01
Default Exp/Contr=0,0
English Units
Geom File=g01
Flow File=f01
Plan File=p01
BEGIN DESCRIPTION:
---------- MODELED AS PART OF WVEMD CTP PROGRAM, 2023----------
Stream Name: Peach Fork
Flood Zone:  AFH
Wetzel County, WV
HEC-RAS Version: RAS 6.3
Vertical Datum: NAVD88
Projection: NAD 1983 StatePlane West Virginia S FIPS 4702 (US Feet)
Terrain: 1-meter West Virginia FEMA R3 South Central (collected 2018-2020)
Land Use: 2019 NLCD
Hydrologic Method:
WV 2010 Regional Regression Equations
Additional Model Notes:
KWSE at DS confluence with PNTPLSNTCK
END DESCRIPTION:
DSS Export Rating Curves= 0
DSS Export Rating Curve Sorted= 0
DSS Export Volume Flow Curves= 0
DXF OffsetX= 0
DXF OffsetY= 0
DXF ScaleX= 0
DXF ScaleY= 0

--- PEACHFK.p01 (plan) ---

Plan Title=Floodplain
Program Version=6.30
Short Identifier=Floodplain
Geom File=g01
Flow File=f01
Subcritical Flow
K Sum by GR= 0
Std Step Tol= 0.01
Critical Tol= 0.01
Num of Std Step Trials= 20
Max Error Tol= 0.3
Flow Tol Ratio= 0.001
Split Flow NTrial= 30
Split Flow Tol= 0.02
Split Flow Ratio= 0.02
Log Output Level= 0
Friction Slope Method= 1
Unsteady Friction Slope Method= 2
Unsteady Bridges Friction Slope Method= 1
Parabolic Critical Depth
Global Vel Dist= 0 , 0 , 0
Global Log Level= 0
CheckData=True
Encroach Param=-1 ,0,0, 0
Mapping Interval=1HOUR
Computation Time Step Use Courant=        0
Computation Time Step Use Time Series=    0
Computation Time Step Count To Double=0
Computation Time Step Max Doubling=0
Computation Time Step Max Halving=0
Computation Time Step Residence Courant=0
Run HTab= 0
Run UNet= 0
Run Sediment= 0
Run PostProcess= 0
Run WQNet= 0
Run RASMapper= 0
UNET Theta= 0
UNET Theta Warmup= 0
UNET ZTol= 0
UNET ZSATol= 0
UNET MxIter= 0
UNET Max Iter WO Improvement= 0
UNET MaxInSteps= 0
UNET DtIC= 0
UNET DtMin= 0
UNET MaxCRTS= 0
UNET WFStab= 0
UNET SFStab= 0
UNET WFX= 1
UNET SFX= 1
UNET Gravity=32.17405
UNET 1D Methodology=Finite Difference
UNET DSS MLevel= 1
UNET Pardiso=0
UNET DZMax Abort= 0
UNET Use Existing IB Tables= 0
UNET Froude Reduction=False
UNET Froude Limit= 0
UNET Froude Power= 0
UNET D1 Cores= 0
UNET WindReference=Eulerian
UNET WindDragFormulation=Hsu (1988)
UNET D2 Coriolis=0
UNET D2 Cores= 0
UNET D2 Theta= 1
UNET D2 Theta Warmup= 1
UNET D2 Z Tol= 0.01
UNET D2 Volume Tol= 0.01
UNET D2 Max Iterations= 20
UNET D2 Equation= 0
UNET D2 RampUpFraction=0.1
UNET D2 TimeSlices= 1
UNET D2 Turbulence Formulation=Non-Conservative (original)
UNET D2 Eddy Viscosity=0.3
UNET D2 Transverse Eddy Viscosity=0.1
UNET D2 Smagorinsky Mixing=0
UNET D2 BCVolumeCheck=0
UNET D2 Cores=0
UNET D2 SolverType=PARDISO (Direct)
UNET D2 Minimum Iterations= 3
UNET D2 Maximum Iterations= 30
UNET D2 Restart Number= 10
UNET D2 Relaxation Coeff=1.3
UNET D2 SOR Precondition Iterations= 10
UNET D2 ILUT Maximum Fill= 8
UNET D2 ILUT Tolerance=1E-08
UNET D2 Convergence Tolerance=0.00001
UNET D1D2 MaxIter= 0
UNET D1D2 ZTol=0.01
UNET D1D2 QTol=0.1
UNET D1D2 MinQTol=1
Write IC File= 0
Write IC File at Fixed DateTime=0
Write IC File at Sim End=0
Echo Input=False
Echo Parameters=False
Echo Output=False
Write Detailed= 0
HDF Write Warmup=0
HDF Write Time Slices=0
HDF Flush=0
HDF Compression= 1
HDF Chunk Size= 1
HDF Spatial Parts= 1
HDF Use Max Rows=0
HDF Fixed Rows= 1
Calibration Method= 0
Calibration Iterations= 20
Calibration Max Change=0.05
Calibration Tolerance=0.2
Calibration Maximum=1.5
Calibration Minimum=0.5
Calibration Optimization Method= 1
WQ AD Non Conservative
WQ ULTIMATE=-1
WQ Max Comp Step=1HOUR
WQ Output Interval=15MIN
WQ Output Selected Increments= 0
WQ Output face flow=0
WQ Output face velocity=0
WQ Output face area=0
WQ Output face dispersion=0
WQ Output cell volume=0
WQ Output cell surface area=0
WQ Output cell continuity=0
WQ Output cumulative cell continuity=0
WQ Output face conc=0
WQ Output face dconc_dx=0
WQ Output face courant=0
WQ Output face peclet=0
WQ Output face adv mass=0
WQ Output face disp mass=0
WQ Output cell mass=0
WQ Output cell source sink temp=0
WQ Output nsm pathways=0
WQ Output nsm derived pathways=0
WQ Create Restart=0
WQ Fixed Restart=0
WQ System Summary=0
WQ Write To DSS=0
Sorting and Armoring Iterations= 10
XS Update Threshold= 0.02
Bed Roughness Predictor= 0
Hydraulics Update Threshold= 0.02
Energy Slope Method= 1
Volume Change Method= 1
Sediment Retention Method= 0
Sediment TS Multiplier= 1
Warm Up Method= 0
XS Weighting Method= 0
Number of US Weighted Cross Sections= 1
Number of DS Weighted Cross Sections= 1
Upstream XS Weight=0
Main XS Weight=1
Downstream XS Weight=0
Number of DS XS's Weighted with US Boundary= 1
Upstream Boundary Weight= 1
Weight of XSs Associated with US Boundary= 0
Number of US XS's Weighted with DS Boundary= 1
Downstream Boundary Weight= 0.5
Weight of XSs Associated with DS Boundary= 0.5
Percentile Method= 0
Sediment Output Level= 3
Mass or Volume Output= 0
Output Increment Type= 1
Profile and TS Output Increment= 1
Transport Output Increment 1
XS Output Flag= 0
XS Output Increment= 10
Read HDF5 Sediment Hotstart= 0
Sediment Hotstart Type= 0
Write Gradation File= 0
Read Gradation Hotstart= 0
Write HDF5 File= 1
Write Binary Output= 1
Write DSS Sediment File= 0
DSS Sediment Output Type= 1
SV Curve= 0
Specific Gage Flag= 0
Subcell Erosion Methods= 0
Subcell Deposition Methods= 0
Advection Scheme= 1
Matrix Solver= 0
Implicit Weighting Factor= 1
Maximum Outer Loop Convergence Iterations= 5
Convergence Maximum Absolute= 0.001
Convergence RMSE= 0.0001
Grain Fractions Max Abs Error= 0.001
Max Subgrid Regions= 1
Max Subgrid Length Scale= 3.402823E+38
Initial Layer Thickness= 3.402823E+38
Min Layer Thickness= 3.402823E+38
Max Layer Thickness= 3.402823E+38
Number of Layers= 5

--- PEACHFK.f01 (steady flow) ---

Flow Title=Flow
Program Version=6.30
Number of Profiles= 1
Profile Names=F01pct
River Rch & RM=PEACHFK,Main            ,4014
     762
River Rch & RM=PEACHFK,Main            ,0
    1110
Boundary for River Rch & Prof#=PEACHFK,Main            , 1
Up Type= 0
Dn Type= 1
Dn Known WS=803.25
DSS Import GetInterval= 0
DSS Import GetPeak= 0
DSS Import FillOption= 0

--- PEACHFK.g01 (geometry) ---

Geom Title=Geometry
Program Version=6.30

River Reach=PEACHFK         ,Main
Reach XY= 30
 1583525.4759988401764.6910033231583281.88865422401833.271346584
1583268.00964735401986.4792035071583174.47229372401997.987726063
1583074.07786091402139.4667962491583010.19089402402184.221528977
1582915.26114766402359.4229130151582973.70726836402420.955528185
1582869.00348632402503.0698129531582837.65960795402578.329280779
1582791.80917194402583.282861352  1582798.316957 402512.21810694
1582749.41200219402509.5295355321582745.19658582402576.772868812
1582683.68996479402535.1081217531582628.57300587402620.356888592
1582430.72661582402687.8621758671582290.63231808402793.671076164
1582267.54402907402883.4358628841582230.86122487 402899.85455884
1582145.66187349402878.8146624421582085.65945995402965.527804703
1581811.68453576403103.7562709751581779.56937733403217.987869412
1581721.87644997403211.8566375081581625.58153965403275.253007472
1581520.12570675403290.1214572341581420.01195078403340.907995775
1580926.34547926403460.7306717041580729.47010033403435.676808968

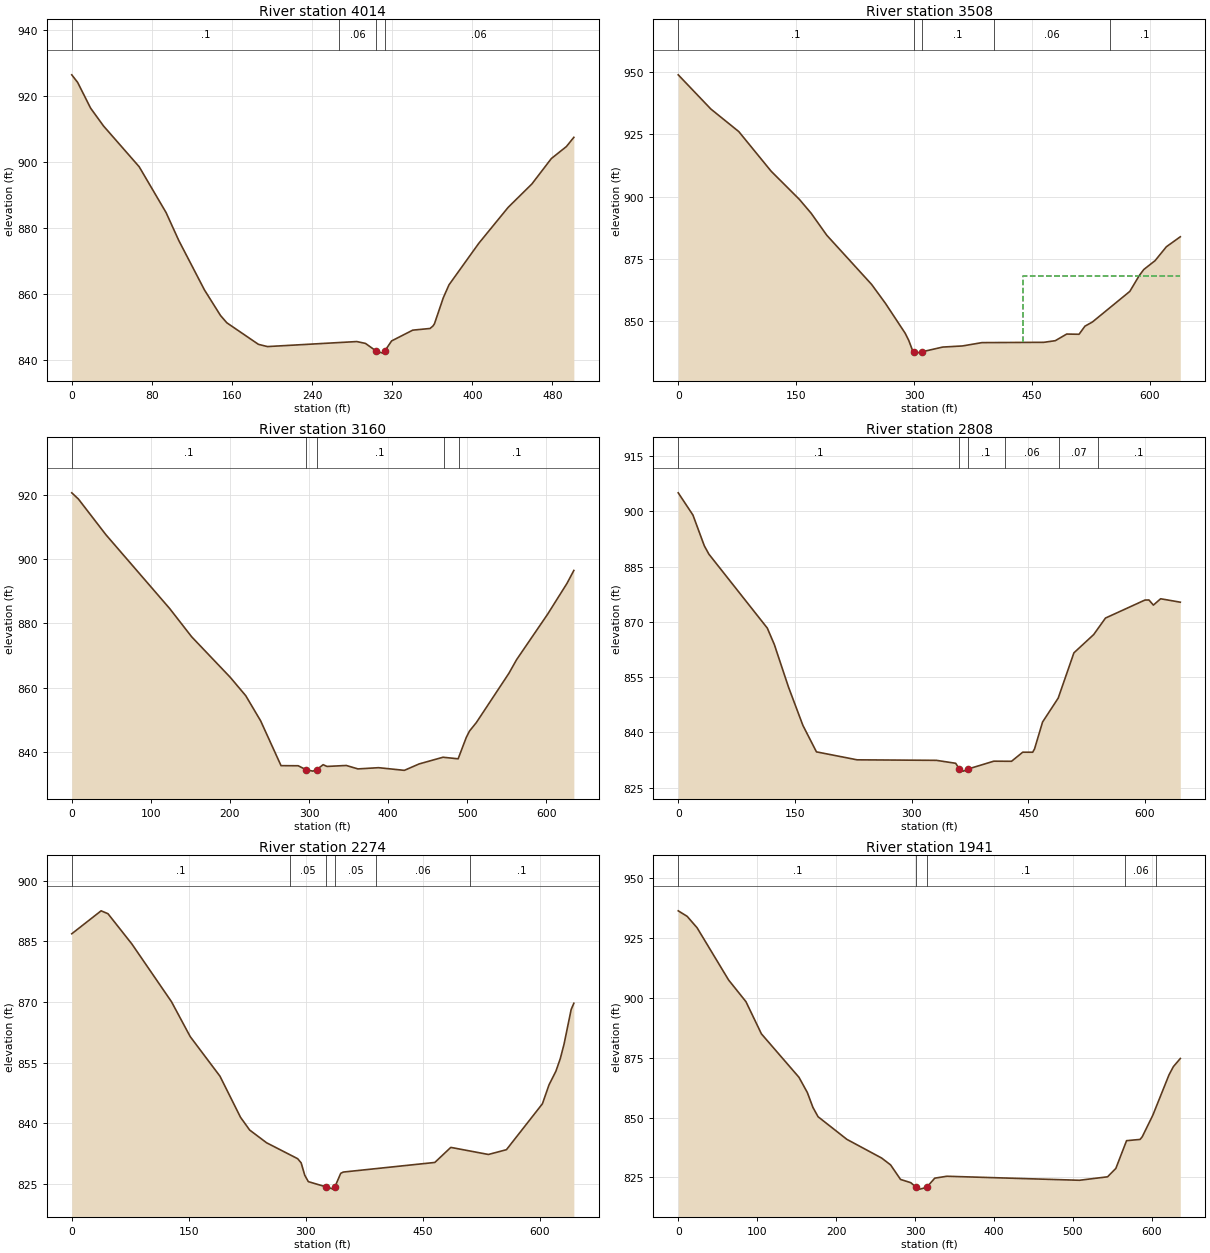
Type RM Length L Ch R = 1 ,4014    ,505.6,506.5,504.4
XS GIS Cut Line= 6
1583386.02436909401491.0752686711583421.04824917 401578.51341401
1583461.11870709401656.3839931791583495.55466184401723.123689085
1583535.34428042401814.9138598441583666.06468957401876.525746883
#Sta/Elev= 30
       0  926.29     5.9  923.98    18.8  916.22    31.7  910.82    67.3  898.49
    94.2  884.61   106.9  876.15   132.5  861.22   148.5  853.49   154.9  851.26
   186.4  844.75   195.4  844.07   284.6  845.59   293.3  845.03  304.29842.6547
   310.7  842.09   312.4  842.65   319.4  845.78   340.5  849.04   357.8  849.55
   360.7  850.29   362.2  850.97     371  858.82   376.7  862.74   406.4  875.29
   435.8  886.19   459.5  893.27   478.9  900.95     494   904.6   501.4  907.38
#Mann= 4 ,-1,0
       0      .1       0  266.87     .06       0  304.29    .045       0
   312.4     .06       0
Bank Sta=304.29,312.4
XS Rating Curve= 0 ,0
Exp/Cntr(USF)=0,0
Exp/Cntr=0.3,0.1

Type RM Length L Ch R = 1 ,3508    ,349.6,347.9,345.3
XS GIS Cut Line= 6
1582972.85590409401773.2997698341583046.40726617401834.366904929
1583107.61055584401897.8582477571583150.95725392401959.056944251
1583244.95411317402119.3725685031583352.69963259402280.573033512
#Sta/Elev= 30
       0  949.02    41.5  935.25      77  926.18   118.1  910.25   154.2  898.84
   169.1  893.28   188.9  884.46   245.9  864.67   263.6  857.01   288.6  845.02
   293.2  842.11   297.9  838.18   299.7  837.53   302.6  836.99  309.95 837.515
   336.4  839.43   361.5  839.88   386.3  841.22   465.1  841.34   479.6     842
   494.1  844.67   509.8  844.58   517.3  847.84   526.8  849.52   574.4  861.85
   586.4  868.22   592.1  870.64   606.5  874.21   620.9  879.82   638.6  883.83
#Mann= 5 ,-1,0
       0      .1       0   299.7    .045       0  309.95      .1       0
  402.23     .06       0  549.16      .1       0
#XS Ineff= 2 , 0
                          438.17          867.91
Permanent Ineff=
       F       F
Bank Sta=299.7,309.95
XS Rating Curve= 0 ,0
Exp/Cntr(USF)=0,0
Exp/Cntr=0.3,0.1

Type RM Length L Ch R = 1 ,3160    ,347.5,351.6,348.5
XS GIS Cut Line= 2
 1582724.2689393402095.6980858191583243.31468539402461.159038013
#Sta/Elev= 30
       0  920.63     8.4   918.7    43.1  907.62   123.9  884.61   151.5  875.88
   200.4  863.25     220  857.53   238.8  849.72   264.6  835.78   286.3  835.75
   296.2  834.53   304.8  834.08  309.68834.5432   317.8  836.08   322.7  835.54
   347.1  835.84   361.8  834.77     388  835.15   420.5  834.32   439.2  836.32
   469.4   838.4   488.5  837.91   498.8  844.56   502.9  846.55   511.5  849.17
   552.6  864.47   562.4  868.74   601.5  882.83     626  892.41   634.8  896.49
#Mann= 5 ,-1,0
       0      .1       0   296.2    .045       0  309.68      .1       0
     470     .06       0     490      .1       0
Bank Sta=296.2,309.68
XS Rating Curve= 0 ,0
Exp/Cntr(USF)=0,0
Exp/Cntr=0.3,0.1

Type RM Length L Ch R = 1 ,2808    ,522.7,533.8,531.8
XS GIS Cut Line= 3
1582631.04128894402232.1037317531582712.38803322402380.882645632
1583088.08154957402673.088713899
#Sta/Elev= 30
       0  905.07    18.9  899.04    33.5   890.7    39.4  888.42   114.5  868.34
   123.6  863.85   141.8  852.29   160.3   841.9   177.7  834.72     230  832.56
   331.9  832.42   356.7  831.62  361.57830.0285   366.8  829.49   371.9  830.02
   405.7  832.19   428.5  832.16   442.9  834.63   455.7  834.62   458.1  835.53
   468.4  842.82   488.5  849.32   508.7  861.61   534.1  866.57   549.3  871.06
     600  875.95   605.2  875.97   610.9  874.58   620.2   876.3   645.5  875.37
#Mann= 6 ,-1,0
       0      .1       0  361.57    .045       0   371.9      .1       0
  419.57     .06       0  489.57     .07       0  539.57      .1       0
Bank Sta=361.57,371.9
XS Rating Curve= 0 ,0
Exp/Cntr(USF)=0,0
Exp/Cntr=0.3,0.1

Type RM Length L Ch R = 1 ,2274    ,334,333.7,332.4
XS GIS Cut Line= 2
 1582455.5035776402333.7871621021582776.60914713402891.440501176
#Sta/Elev= 30
       0  886.85    37.6  892.52    46.4  891.81      77  884.34   127.8  870.07
   151.8  861.45   189.9  851.68   216.3  841.51     228  838.37   249.7  835.22
   289.5  831.29     294  830.26   298.6  827.21   303.2  825.62   326.3   824.3
   335.5  823.77  337.32 824.361   344.7  827.67   348.1  827.99   465.3  830.36
   485.8  834.08     534  832.33   557.1  833.51   603.2  844.85   611.7  849.54
   620.5   852.9   626.1  855.99   630.9  859.55   640.1  868.17   643.5  869.68
#Mann= 6 ,-1,0
       0      .1       0     280     .05       0   326.3    .045       0
  337.32     .05       0     390     .06       0     510      .1       0
Bank Sta=326.3,337.32
XS Rating Curve= 0 ,0
Exp/Cntr(USF)=0,0
Exp/Cntr=0.3,0.1

Type RM Length L Ch R = 1 ,1941    ,428.2,434.1,434
XS GIS Cut Line= 6
1582143.52325661 402523.62469155 1582254.5765122402666.868171472
 1582361.8007072402805.1720287091582407.75402736402864.444876049
1582466.49800435402938.5531941831582537.26024048403023.288797423
#Sta/Elev= 30
       0  936.42    11.3  934.12    23.9  929.34    63.8  907.53    85.8  898.46
   105.4  885.01     153  866.85   163.6  860.49   170.7  854.25   177.2  850.37
   213.7  840.92   257.7  833.12   269.1  830.24   281.7  824.17   294.7  822.81
  301.77820.8084   306.1  820.12   314.7  820.83   325.1  824.71   340.4   825.5
   508.4  823.82     544  825.27   554.5  828.76   568.1  840.37   585.2  840.89
     588  842.02   601.4  851.03   621.9  867.89   627.4  871.31   636.2  874.71
#Mann= 5 ,-1,0
       0      .1       0  301.77    .045       0   314.7      .1       0
  565.82     .06       0  605.82      .1       0
Bank Sta=301.77,314.7
XS Rating Curve= 0 ,0
Exp/Cntr(USF)=0,0
Exp/Cntr=0.3,0.1

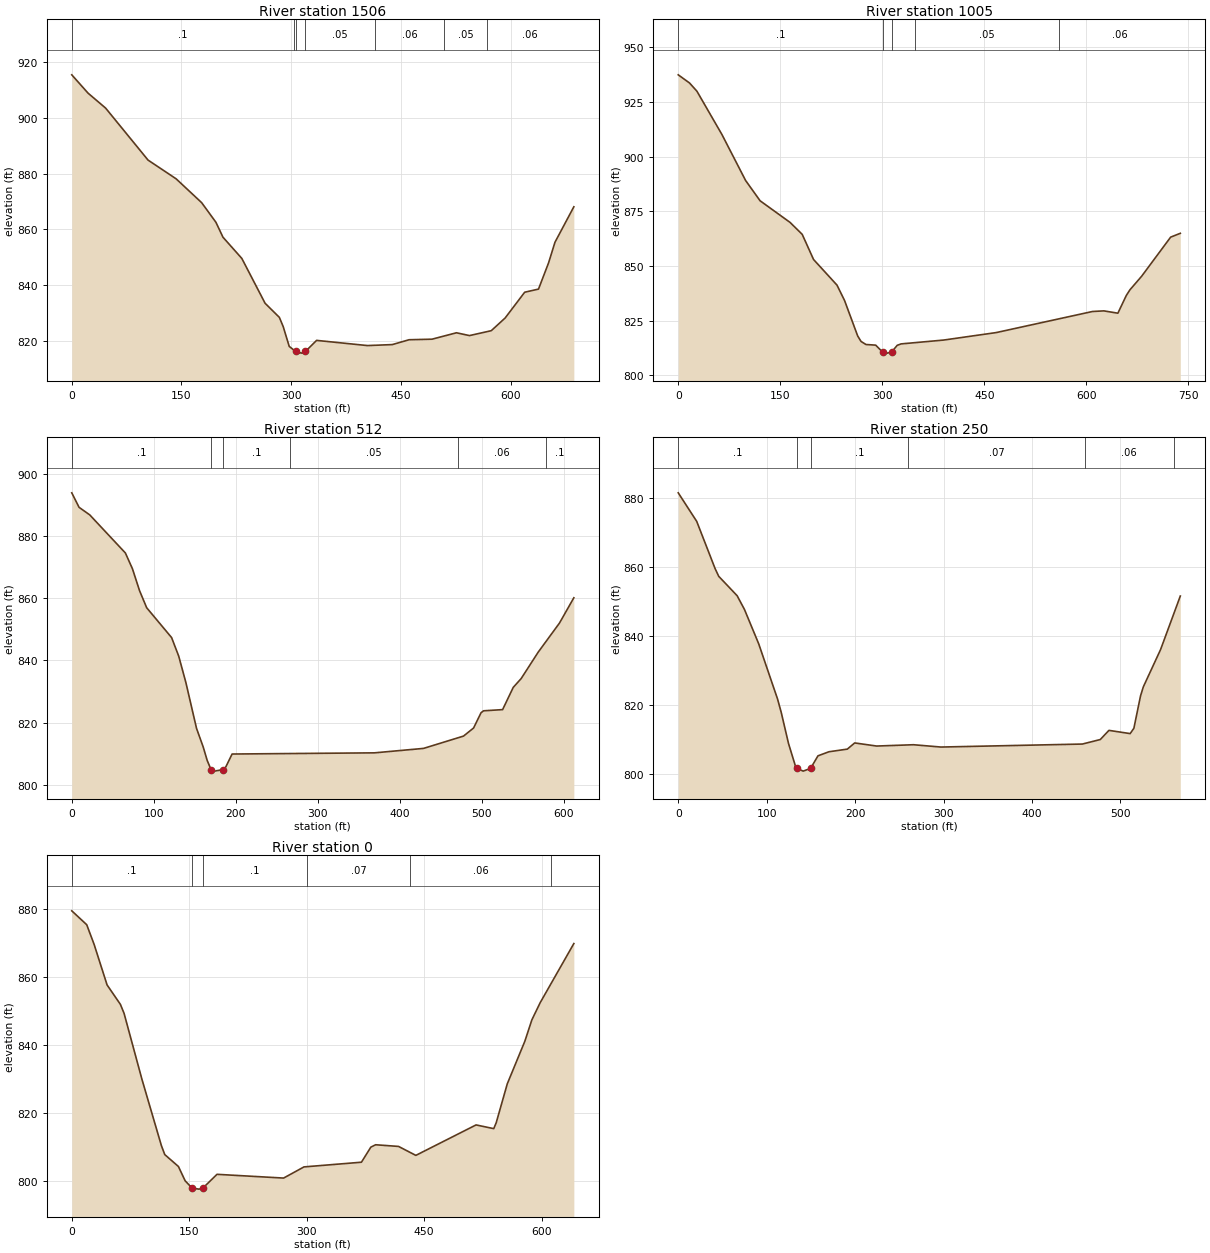
Type RM Length L Ch R = 1 ,1506    ,502.5,501.5,498.2
XS GIS Cut Line= 6
1581876.94044501402714.7788580061581989.38411775402863.877313092
  1582031.715726402928.2836803351582077.88394076403097.601911262
1582102.97969109 403181.824839921582175.62784139403323.470415488
#Sta/Elev= 30
       0  915.46    22.3  908.88    46.3  903.52   104.3  884.87   142.7  878.15
   177.6  869.59   197.1  862.55   206.7  857.21   232.5  849.59   264.3  833.51
   283.8  828.45     289  825.18   297.3  818.03  305.92816.2408     314  815.62
   319.5  816.23   334.7  820.19   404.2  818.33   438.2  818.68   461.1  820.42
   492.5  820.62   525.9  822.92   543.7  821.91   573.5  823.67   592.5  828.23
   619.2  837.47   638.1  838.59   651.9  848.04   660.6   855.4   686.4  868.12
#Mann= 7 ,-1,0
       0      .1       0  303.82     .05       0  305.92    .045       0
   319.5     .05       0  413.97     .06       0  509.33     .05       0
  567.21     .06       0
Bank Sta=305.92,319.5
XS Rating Curve= 0 ,0
Exp/Cntr(USF)=0,0
Exp/Cntr=0.3,0.1

Type RM Length L Ch R = 1 ,1005    ,490.3,492.8,493.2
XS GIS Cut Line= 6
1581518.34897059402972.042779177 1581604.8720915403133.050331175
1581709.20423192403273.7629762591581770.53547409403433.690477923
1581811.82897082403511.0372314281581925.50641953403553.226800019
#Sta/Elev= 30
       0  937.42    16.6  933.69    27.4  929.96    64.3  910.09    99.1  889.06
   120.4  879.79   164.4  869.91   182.3  864.44     199  852.93   233.5  841.19
   244.6  834.15   263.9  817.94   268.8  815.45     276  814.04   290.4  813.74
   300.4  810.59   307.6  810.09  313.81810.5993     322  813.66   327.7  814.31
   390.4  816.07   467.7   819.5   609.2  829.14   625.9  829.42   646.5  828.36
   658.9  836.48   664.3  839.09   681.4  845.25   724.1  863.16   738.3  864.91
#Mann= 5 ,-1,0
       0      .1       0   300.4    .045       0  313.81      .1       0
  347.87     .05       0  559.41     .06       0
Bank Sta=300.4,313.81
XS Rating Curve= 0 ,0
Exp/Cntr(USF)=0,0
Exp/Cntr=0.3,0.1

Type RM Length L Ch R = 1 ,512     ,260.9,262.1,262.8
XS GIS Cut Line= 6
1581158.16943432403220.315140637 1581257.8037495403456.402266877
1581296.68490534403548.5339723851581325.84593624403617.632587465
1581359.86686558403698.2479117981581396.31758007403784.621754798
#Sta/Elev= 30
       0  894.02     8.9  889.35    21.9  886.92    65.4  874.64      74  869.57
    82.7  862.48    91.4  856.99   121.8  847.37   130.5  841.37   139.2   832.9
   152.2  818.12   160.4  812.08   165.2   807.8  169.88804.8417   173.9  804.34
   184.8  804.84   187.9  805.69   195.6  809.85   369.3  810.23   429.1  811.66
   477.9  815.63   490.2  818.24   499.3  823.16   502.4  823.78   525.6  824.16
   538.6  831.34   548.2  834.15     569  842.67     595  852.06   612.5   860.2
#Mann= 6 ,-1,0
       0      .1       0  169.88    .045       0   184.8      .1       0
  266.25     .05       0  471.25     .06       0  578.75      .1       0
Bank Sta=169.88,184.8
XS Rating Curve= 0 ,0
Exp/Cntr(USF)=0,0
Exp/Cntr=0.3,0.1

Type RM Length L Ch R = 1 ,250     ,244.9,250,254.8
XS GIS Cut Line= 2
  1580936.101745 403312.415237651581089.03692714403859.106612712
#Sta/Elev= 30
       0  881.64    20.9  873.35    41.7  859.64    45.8   857.4    66.6  851.78
    74.9  847.78      91  837.81   112.3  821.79   116.4  817.97   124.7  808.88
     133  801.92  134.09801.6812   141.3  800.86   149.7  801.67     158   805.3
   170.4  806.48   191.2  807.25   199.5  809.04   224.4  808.14     266  808.52
     297  807.85     457  808.72   477.2  810.03     487  812.69     511  811.75
   515.2   813.3   522.7  822.67   525.9  825.33   545.4  836.15   567.7  851.68
#Mann= 6 ,-1,0
       0      .1       0  134.09    .045       0   149.7      .1       0
     260     .07       0     460     .06       0     560      .1       0
Bank Sta=134.09,149.7
XS Rating Curve= 0 ,0
Exp/Cntr(USF)=0,0
Exp/Cntr=0.3,0.1

Type RM Length L Ch R = 1 ,0       ,580.2,583.9,585.7
XS GIS Cut Line= 3
1580791.79414884403286.959460952 1580663.3414619403593.472651258
1580419.30171765403782.876631873
#Sta/Elev= 30
       0   879.5    19.1  875.42    28.5  869.66    45.1  857.72    62.1  852.01
    66.8  849.37    89.6  830.01   114.5  810.47   118.8  807.85   136.2  804.36
   144.8  800.16   153.5  798.04   162.2   797.7  167.61798.0378   185.5  802.05
   270.6  800.95   296.6  804.23     370  805.61     382  810.04   388.1  810.74
   417.4  810.25   439.5  807.62   516.4  816.57     539  815.48   542.1  817.19
   556.3  828.66   578.7  841.16   587.7  847.46   598.3   852.5   641.3  869.88
#Mann= 6 ,-1,0
       0      .1       0   153.5    .045       0  167.61      .1       0
     300     .07       0  432.34     .06       0  612.34      .1       0
Bank Sta=153.5,167.61
XS Rating Curve= 0 ,0
Exp/Cntr=0.3,0.1
LCMann Table=0

Chan Stop Cuts=-1
Use User Specified Reach Order=0
Composite Channel Slope=5